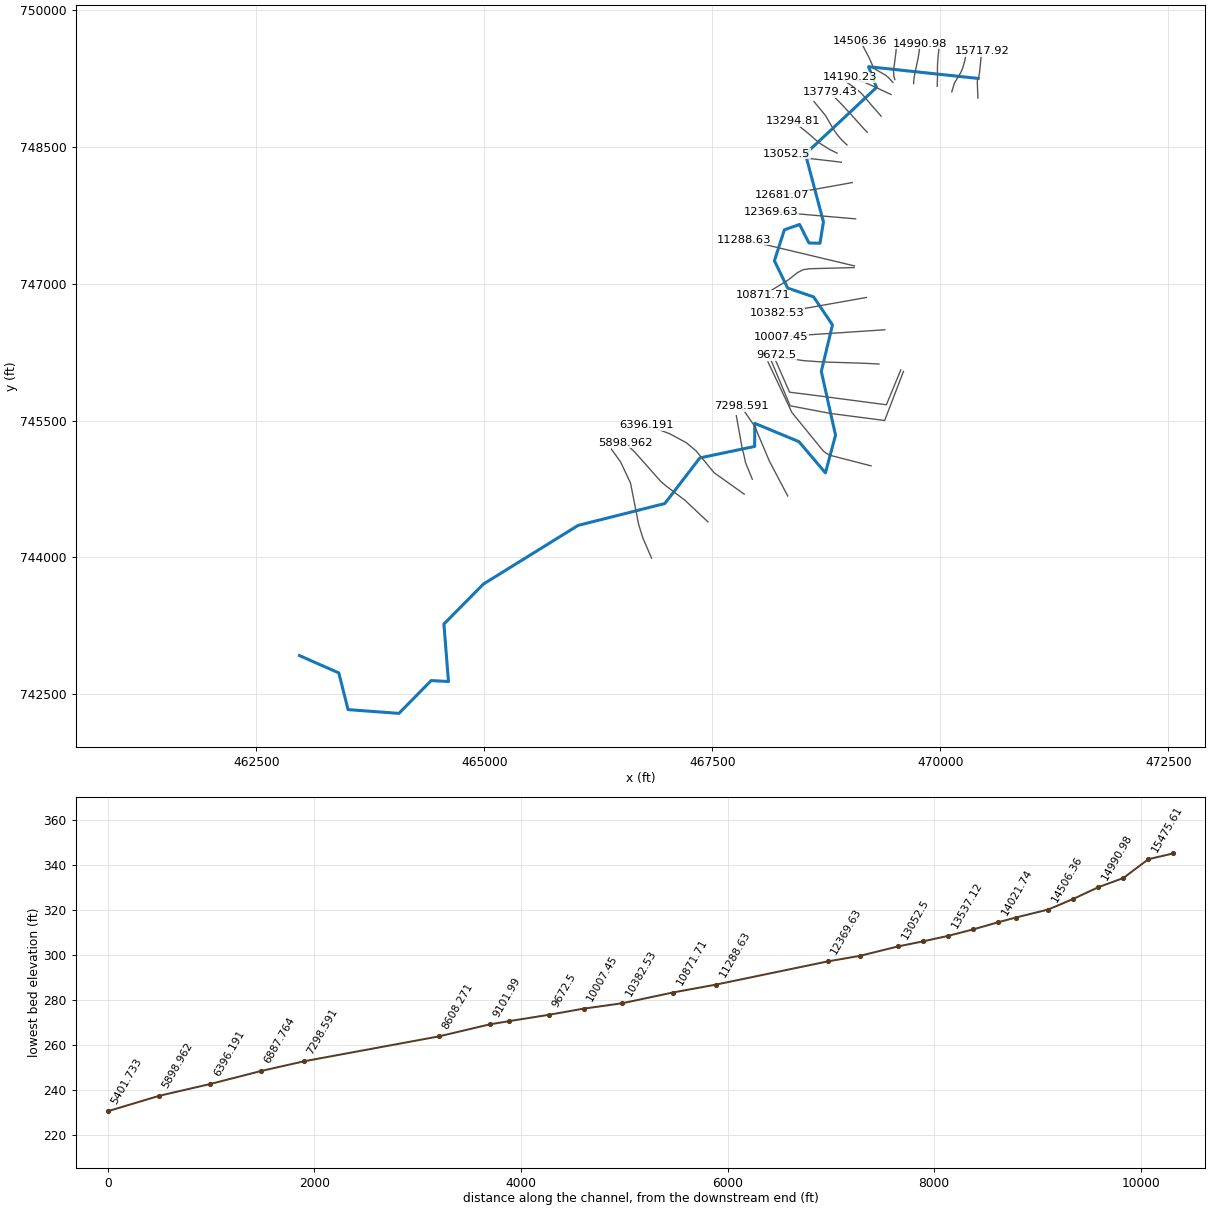
--- 2587_ras.prj (project) ---

Proj Title=2587
Current Plan=p01
Default Exp/Contr=0.3,0.1
English Units
Geom File=g01
Flow File=f01
Plan File=p01
Y Axis Title=Elevation
X Axis Title(PF)=Main Channel Distance
X Axis Title(XS)=Station
BEGIN DESCRIPTION:
RFD model 2587 exported to HEC-RAS
END DESCRIPTION:

--- 2587_ras.p01 (plan) ---

Plan Title=Plan 01
Program Version=4.10
Short Identifier=Plan 01
Geom File=g01
Flow File=f01
Subcritical Flow
Calc Critical at every XS
Secant Critical Depth

--- 2587_ras.f01 (steady flow) ---

Flow Title=Flow 01
Program Version=5.01
Number of Profiles= 6
Profile Names=10yr,25yr,50yr,100yr,100plus,500yr
River Rch & RM=2587,27,15717.92
 1155.48 2001.73 2851.05 3692.81  5391.5 7706.36
River Rch & RM=2587,27,15475.61
 1161.37 2012.95 2867.99 3715.85 5425.15 7752.77
River Rch & RM=2587,27,15233.29
 1162.98    2016 2872.58 3722.07 5434.23  7765.2
River Rch & RM=2587,27,14990.98
 1165.18 2020.15 2878.82 3730.55  5446.6 7782.14
River Rch & RM=2587,27,14748.67
  1169.1 2027.59 2890.03 3745.76 5468.81 7812.59
River Rch & RM=2587,27,14506.36
  1181.7 2051.58 2926.23 3795.02 5540.72 7911.53
River Rch & RM=2587,27,14190.23
 1182.27 2052.66 2927.86 3797.24 5543.98 7916.02
River Rch & RM=2587,27,14021.74
 1184.81 2057.52 2935.22 3807.26 5558.61 7936.19
River Rch & RM=2587,27,13779.43
  1186.6 2060.97 2940.45 3814.43 5569.07 7950.75
River Rch & RM=2587,27,13537.12
 1214.04 2114.07 3021.37  3925.4 5731.08 8176.72
River Rch & RM=2587,27,13294.81
 1215.63 2117.16  3026.1  3931.9 5740.57    8190
River Rch & RM=2587,27, 13052.5
 1217.61 2121.03    3032 3940.02 5752.43 8206.59
River Rch & RM=2587,27,12681.07
 1220.26 2126.18 3039.88 3950.84 5768.23 8228.69
River Rch & RM=2587,27,12369.63
 1223.31  2132.1 3048.93 3963.28 5786.39 8254.07
River Rch & RM=2587,27,11288.63
 1228.64 2142.53 3064.91 3985.31 5818.56 8299.25
River Rch & RM=2587,27,10871.71
 1232.86 2150.91 3077.87 4003.29 5844.81 8336.63
River Rch & RM=2587,27,10382.53
 1236.35 2157.83 3088.55 4018.11 5866.44 8367.38
River Rch & RM=2587,27,10007.45
  1258.5 2201.37 3155.48 4110.58 6001.44 8557.43
River Rch & RM=2587,27,  9672.5
 1262.36 2208.99 3167.25 4126.89 6025.26 8591.11
River Rch & RM=2587,27,9285.453
 1268.29 2220.74  3185.4 4152.06 6062.01 8643.17
River Rch & RM=2587,27, 9101.99
 1270.23 2224.61  3191.4  4160.4 6074.19  8660.5
River Rch & RM=2587,27,8608.271
 1280.29 2244.66 3222.46  4203.6 6137.25 8750.15
River Rch & RM=2587,27,7298.591
 1289.97 2263.94 3252.32 4245.12 6197.87 8836.22
River Rch & RM=2587,27,6887.764
    1292 2268.01 3258.63 4253.91  6210.7 8854.47
River Rch & RM=2587,27,6396.191
 1295.11 2274.22 3268.27 4267.33 6230.31 8882.35
Boundary for River Rch & Prof#=2587,27,1
Up Type= 0
Dn Type= 2
Boundary for River Rch & Prof#=2587,27,2
Up Type= 0
Dn Type= 2
Boundary for River Rch & Prof#=2587,27,2
Up Type= 0
Dn Type= 2
Boundary for River Rch & Prof#=2587,27,2
Up Type= 0
Dn Type= 2
Boundary for River Rch & Prof#=2587,27,2
Up Type= 0
Dn Type= 2
Boundary for River Rch & Prof#=2587,27,2
Up Type= 0
Dn Type= 2

--- 2587_ras.g01 (geometry) ---

Geom Title=2587
Program Version=4.10

River Reach=2587,27
Reach XY= 30
470415.012275973749254.176289189469212.882972181749382.961053625
469300.122555524749155.096470296468520.174638927 748425.92980361
468718.091305524747681.138136938468680.330888838747446.763136938
468559.237138957 747449.36730361468456.372555673747652.492303625
468289.705888838747593.898553625468180.330888987 747254.05480361
468326.164222181746954.575636953468610.018388838746858.221470296
468817.049638838746550.929803625468694.653805524746040.513136953
468850.903805524745341.294386953 468739.79269442744928.099942505
468449.862138838745270.113831401467965.487138838745471.502720281
467963.751027882745218.030498043467362.926375151745092.336053625
466978.228335828744591.863360092466027.117224872744351.863360062
464989.339447081743709.085582301464555.589446872743270.405026764
464605.638169885742639.866382554464415.477579594742649.917019129
464062.352579594742290.420491368 463504.65582034742331.566324696
463402.572487056742734.344102442462972.016931444742923.927435815

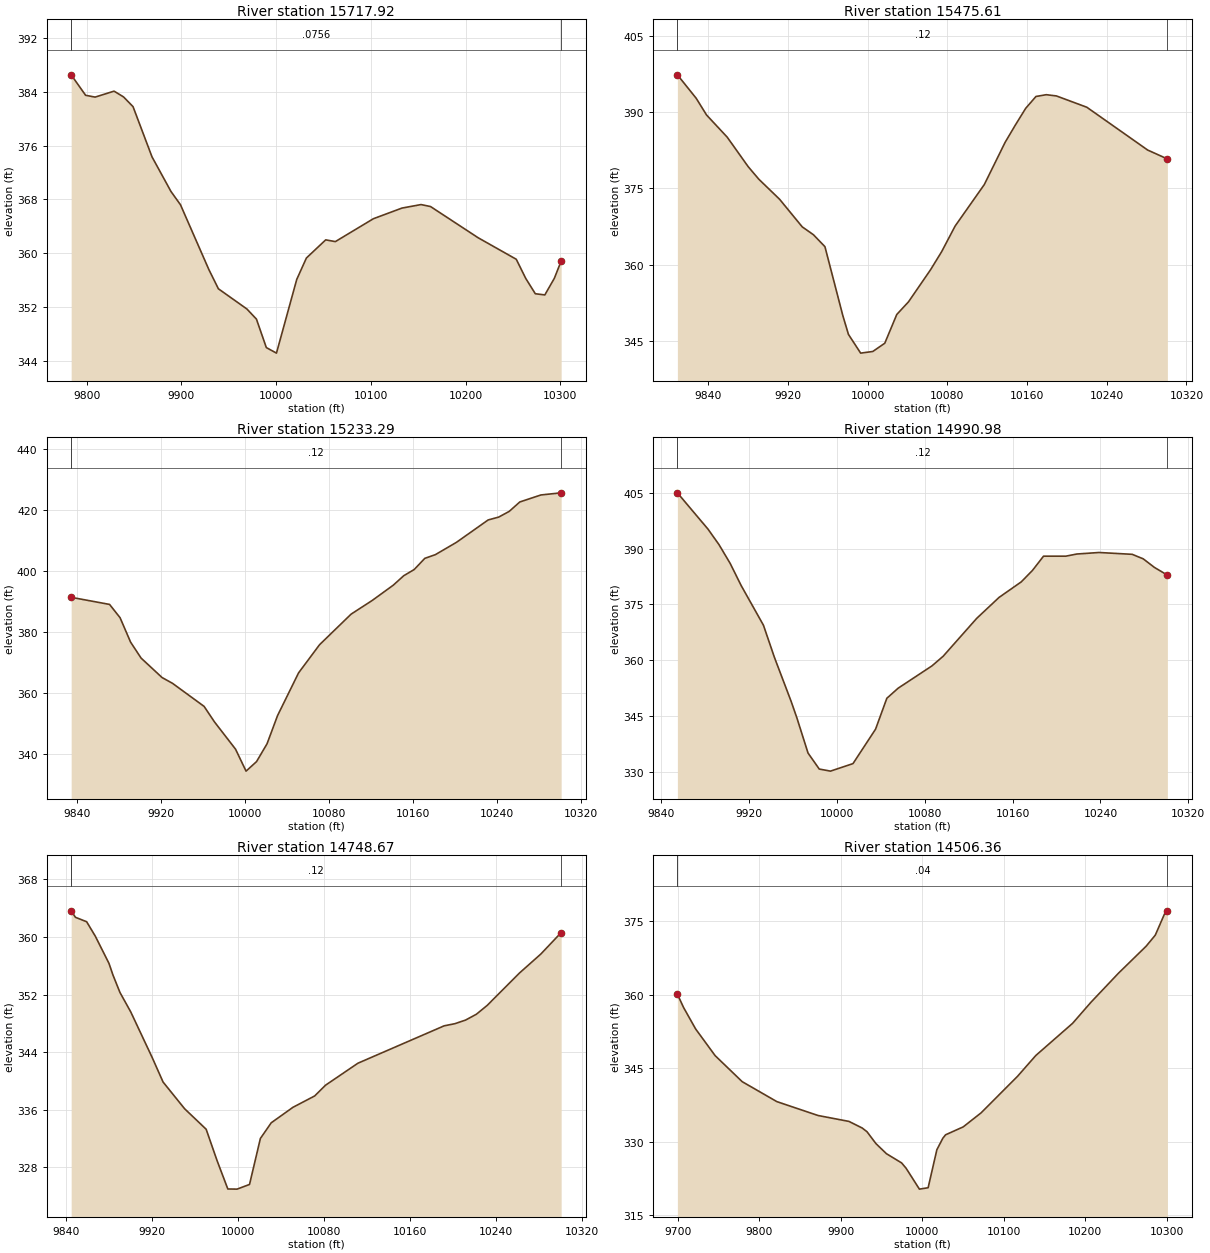
Type RM Length L Ch R = 1 ,15717.92,242.310300,242.310300,242.310300
XS GIS Cut Line= 6
470412.315360643749039.757707893470405.320959406749218.094993085
 470408.29575368749239.069409198470421.885861311 749274.94186822
470429.255122132749312.107847971470453.683910237749552.143443234
#Sta/Elev= 30
9783.719386.48539798.978383.44999808.989383.18089829.012384.06329839.023383.2078
9849.034 381.7649869.056374.31589889.078369.17899899.089367.21549929.121357.5829
9939.122354.74539969.191351.74929979.291350.2447 9989.72346.023810000.43345.1986
10021.83356.130710032.02359.308810052.41362.002410062.57361.742210102.77365.1397
10132.93366.717210153.03367.236610163.08366.942810213.34362.311810253.55359.1237
 10263.6356.270510273.65 354.009 10283.7353.834310293.75356.300510300.94358.8578
#Mann= 3 , 0 , 0
9783.719  0.0756       09783.719  0.0756       010300.94  0.0756       0
#XS Ineff= 2 , 0
       0                               0
Bank Sta=9783.719,10300.94
Exp/Cntr=0.3,0.1

Type RM Length L Ch R = 1 ,15475.61,242.310200,242.310200,242.310200
XS GIS Cut Line= 6
 470125.11789831749106.537991599470155.212576007749205.043718595
470220.461930782749312.158133894470242.007376524749357.252743986
470268.527101805749448.682772168470290.256619964749564.487309542
#Sta/Elev= 30
9808.981397.32389827.861392.71669838.226389.43959859.018385.06889880.035379.2824
9890.724376.81129911.548372.87869934.324367.44419945.452365.91679957.098363.5594
9975.042350.02559980.721346.31099992.957342.634810005.15342.958510017.18344.5797
10029.21350.224710040.97352.707310063.14359.020310074.22362.5538 10087.8367.6062
10117.08375.755210137.96384.045310148.29387.463410158.61390.731110168.94393.0665
10179.26393.418210189.49393.175210220.01390.954310281.06382.546410300.89380.7977
#Mann= 3 , 0 , 0
9808.981    0.12       09808.981    0.12       010300.89    0.12       0
#XS Ineff= 2 , 0
       0                               0
Bank Sta=9808.981,10300.89
Exp/Cntr=0.3,0.1

Type RM Length L Ch R = 1 ,15233.29,242.310300,242.310300,242.310300
XS GIS Cut Line= 6
469965.604521669749168.435206483469968.964365581749261.443436928
469968.298781638749362.907714869469969.696519392749413.304424198
469975.873989095749496.410579072469990.634288142749634.177726226
#Sta/Elev= 30
9834.143391.38079870.731389.04299880.738384.68199890.744 376.6729900.751371.4195
9920.764365.01979930.768 363.1059960.768355.55219970.768350.40489990.769341.4827
10000.77334.274910010.77337.405510020.77343.259310030.77352.507810050.78366.5335
10070.79375.803710100.85385.849410120.91390.331910140.96395.348710150.99398.4684
10161.02400.521410171.07404.181310181.13405.391610201.24409.444910231.41416.7933
10241.47417.736410251.53419.615210261.58422.7055 10281.7 425.00510300.99425.7084
#Mann= 3 , 0 , 0
9834.143    0.12       09834.143    0.12       010300.99    0.12       0
#XS Ineff= 2 , 0
       0                               0
Bank Sta=9834.143,10300.99
Exp/Cntr=0.3,0.1

Type RM Length L Ch R = 1 ,14990.98,242.310200,242.310200,242.310200
XS GIS Cut Line= 6
469706.986304024 749197.15576968469708.965224549749236.053315784
469718.510721503749299.904334972 469757.11924762749479.650730317
469768.097055817749549.996395107469778.655698722749636.793768437
#Sta/Elev= 30
9854.965404.98699882.846395.22319892.859391.05269902.959 386.039 9913.07380.0357
9933.293369.40059943.404360.66079958.474348.95089963.677344.54489973.887335.0365
9984.097330.73829994.308330.179210014.81332.202410035.35341.455510045.62349.7625
10055.89352.466410086.69358.469210096.87361.057910127.43371.246710147.76376.8737
   10168381.057310178.12384.112610188.25387.960810208.49387.958610218.59388.5385
10238.73388.946110268.95388.456510279.03387.2349 10289.1384.953710300.98382.8641
#Mann= 3 , 0 , 0
9854.965    0.12       09854.965    0.12       010300.98    0.12       0
#XS Ineff= 2 , 0
       0                               0
Bank Sta=9854.965,10300.98
Exp/Cntr=0.3,0.1

Type RM Length L Ch R = 1 ,14748.67,242.310300,242.310300,242.310300
XS GIS Cut Line= 6
469501.402175657749241.193133389469490.400340975749278.557442741
469486.598676559749334.579208055469513.897845413 749547.75542876
469518.322654055749621.352867689469519.169036966749693.939995346
#Sta/Elev= 30
9844.457363.63659848.457362.73639858.874362.12289866.991360.10519879.708356.3315
9883.413354.71939889.909352.30399899.993 349.5929920.093343.21889930.093339.8612
9950.128336.15689970.224333.3064 9980.32328.98169990.416325.0102    9999324.9904
10010.63325.639810020.75332.023410030.87334.2031 10051.1336.351910071.33337.9286
10081.45339.421910111.63342.475610191.97347.665910201.98347.9648   10212348.4701
10222.02349.279410232.03350.499910262.03354.983810282.03357.633610300.98360.6155
#Mann= 3 , 0 , 0
9844.457    0.12       09844.457    0.12       010300.98    0.12       0
#XS Ineff= 2 , 0
       0                               0
Bank Sta=9844.457,10300.98
Exp/Cntr=0.3,0.1

Type RM Length L Ch R = 1 ,14506.36,316.136700,316.136700,316.136700
XS GIS Cut Line= 6
469480.161944852749210.778829587469437.877895491 749256.99485195
469398.682215313749290.518640591 469270.28148258749364.279912192
469218.859634839749481.619231115 469121.42468828749668.204173647
#Sta/Elev= 30
9699.251360.11779706.898357.38179721.712352.99789745.634 347.5569778.837342.2394
9821.376338.16269871.983335.3252 9909.95334.11879926.168332.77079932.063332.0148
9943.119329.57559955.958327.52059974.574325.63839980.097324.55089996.444320.2787
10007.16320.560510017.88328.325510025.27330.6903 10028.6331.382510050.24332.9982
10072.22335.870610116.87343.319610139.43347.593510184.56354.162110207.12358.4692
10240.96364.413910274.81369.912510286.09372.174210297.37376.485110300.98377.1554
#Mann= 3 , 0 , 0
9699.251    0.04       09699.251    0.04       010300.98    0.04       0
#XS Ineff= 2 , 0
       0                               0
Bank Sta=9699.251,10300.98
Exp/Cntr=0.3,0.1

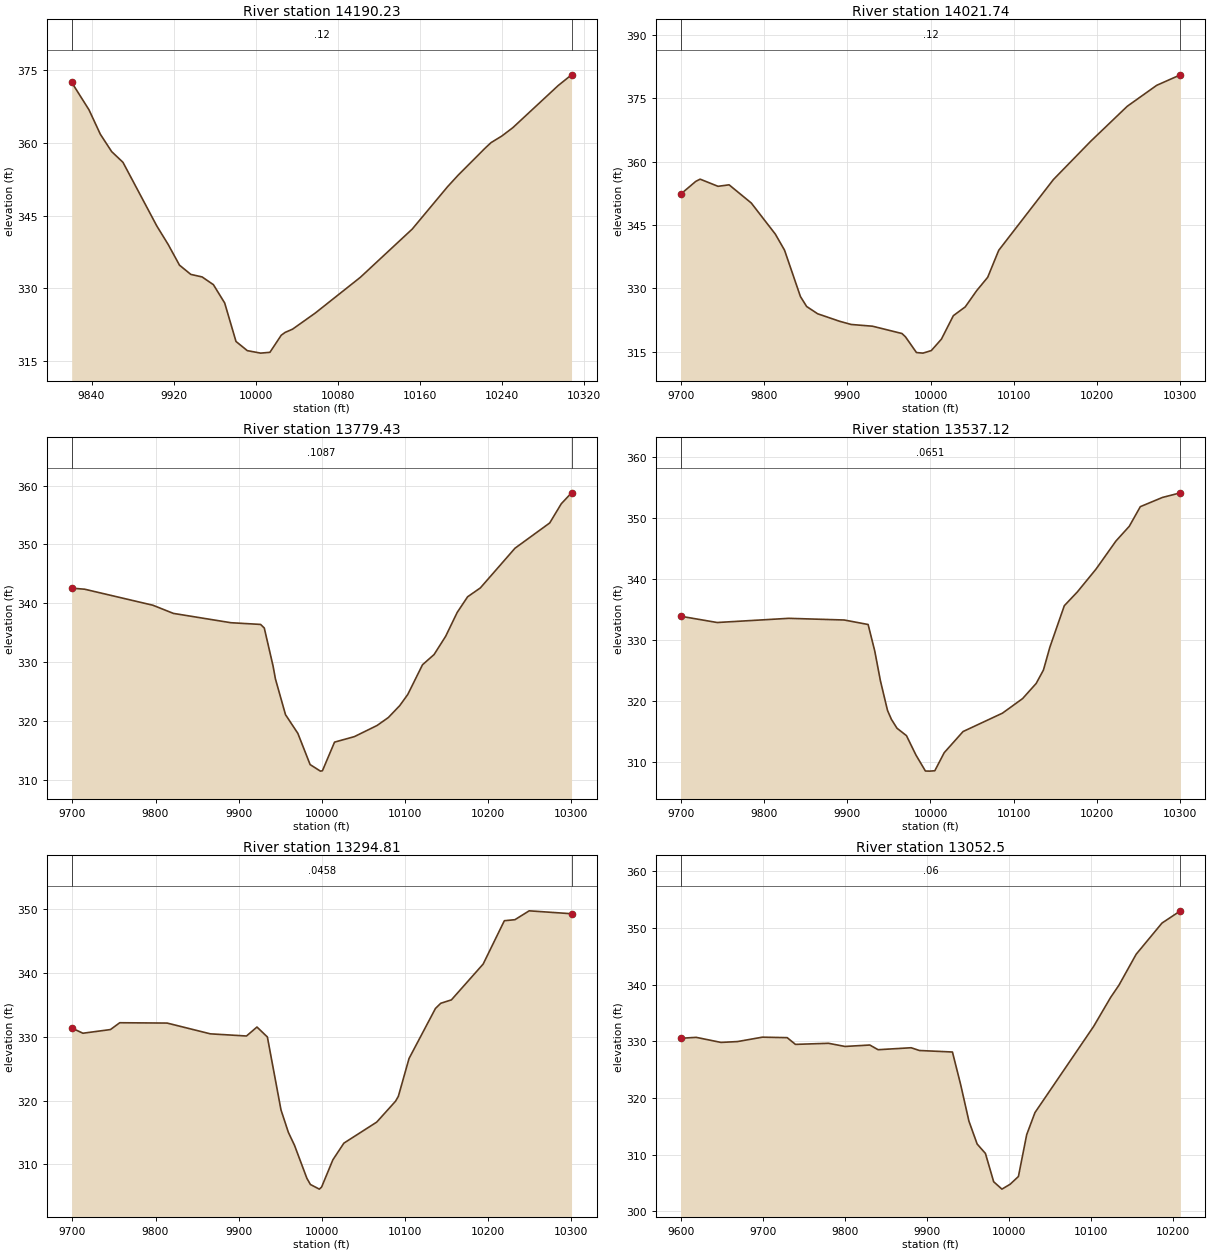
Type RM Length L Ch R = 1 ,14190.23,168.483800,168.483800,168.483800
XS GIS Cut Line= 5
  469460.3722215749077.816959217469169.156907678749212.254889816
469115.385165095749226.063835993469065.914783299749243.770876735
469013.182336211749268.401060387
#Sta/Elev= 30
 9820.65372.40049837.581366.72459848.595361.7196 9859.61358.14819870.624 355.947
9903.666342.8256 9914.68339.04399925.695334.78949936.709332.88779947.723332.3636
9958.737330.77499969.751 326.9979980.765319.08629991.779317.2013 10004.8316.6892
10013.81316.857910024.82320.369510028.66320.956310035.84321.616910057.86324.9123
10101.92332.287310152.44342.205710186.99350.951710197.32353.327710223.43358.8493
10229.19359.986410239.81361.361510250.47363.069610294.62371.727910307.66373.9399
#Mann= 3 , 0 , 0
 9820.65    0.12       0 9820.65    0.12       010307.66    0.12       0
#XS Ineff= 2 , 0
       0                               0
Bank Sta=9820.65,10307.66
Exp/Cntr=0.3,0.1

Type RM Length L Ch R = 1 ,14021.74,242.310300,242.310300,242.310300
XS GIS Cut Line= 6
 469350.64562887748841.207540112469256.376998263748947.765785079
469144.702162679749078.977543485469119.973380624749104.277202955
469060.532978378749152.373415033 468915.50141295749251.048533716
#Sta/Elev= 30
9699.013 352.2559717.428355.32069722.626355.83529744.132354.14089757.483354.4945
9784.186350.18699813.179342.81239824.241339.01599843.389328.02659850.853325.6722
9864.079323.94949890.531322.17149904.506321.4124 9930.21320.99939965.624319.2697
9969.888318.48069983.114314.75859990.989314.6239   10001315.233110013.15 317.938
10027.52323.499710041.82325.573610055.61329.421310068.88332.592310082.15338.9762
10147.97355.736210192.69364.767710236.86373.092110272.41 378.06810300.94380.5515
#Mann= 3 , 0 , 0
9699.013    0.12       09699.013    0.12       010300.94    0.12       0
#XS Ineff= 2 , 0
       0                               0
Bank Sta=9699.013,10300.94
Exp/Cntr=0.3,0.1

Type RM Length L Ch R = 1 ,13779.43,242.310300,242.310300,242.310300
XS GIS Cut Line= 6
469198.402937777748663.675374963469146.898624364748717.742845593
  469021.2595694748858.238753719468996.304306061748885.341610704
468916.486350842748971.217199026 468787.90774972749103.876497797
#Sta/Elev= 30
9699.007342.56299714.647342.3799 9796.83 339.6559821.532338.26629890.737336.6815
9926.544336.38949930.983335.78089941.545329.31899944.398327.11789956.547 321.037
9971.399317.86199986.162312.55629998.536311.4386   10001311.5014 10015.6316.3709
 10039.5 317.308 10066.8319.201310080.45320.5638 10094.1322.581710103.74324.4711
10121.51329.528310135.44331.268110149.36 334.36310163.29338.429410175.85341.0952
10191.14342.596210232.92349.3554 10274.7353.647210288.63356.913510300.99358.7741
#Mann= 3 , 0 , 0
9699.007  0.1087       09699.007  0.1087       010300.99  0.1087       0
#XS Ineff= 2 , 0
       0                               0
Bank Sta=9699.007,10300.99
Exp/Cntr=0.3,0.1

Type RM Length L Ch R = 1 ,13537.12,242.310200,242.310200,242.310200
XS GIS Cut Line= 6
 468976.57596637748525.053455998468921.766846425748575.722724533
468866.376048668748640.674461174468821.365482779748707.463105947
468740.292682012748847.904162617468613.645161606749001.201560783
#Sta/Elev= 30
9699.078333.93019743.193 332.8999829.421333.5835 9896.14333.3109 9924.93332.5745
9932.905328.24539939.689323.39169948.284318.51149952.933317.05939959.688315.6008
9971.091314.38789982.495311.21729993.898   308.6    9999308.581510005.22308.6427
10016.53311.598710039.24315.059610086.66318.066110110.87320.445910127.22322.9199
10135.99325.117110143.75328.863910161.12 335.648 10176.8337.896510199.34341.6423
10223.28346.230110239.33348.640210252.67351.857710279.33353.365710300.93  354.12
#Mann= 3 , 0 , 0
9699.078  0.0651       09699.078  0.0651       010300.93  0.0651       0
#XS Ineff= 2 , 0
       0                               0
Bank Sta=9699.078,10300.93
Exp/Cntr=0.3,0.1

Type RM Length L Ch R = 1 ,13294.81,242.310300,242.310300,242.310300
XS GIS Cut Line= 6
468867.233843395748435.035219748468782.062323409748477.409522521
468689.836767821748535.921643682468640.672399957748573.783804401
468540.552966135 748660.84732579468381.547011352748786.666392004
#Sta/Elev= 30
9699.041331.40879712.572330.58129745.752331.15829756.939332.22749814.023332.1758
9865.987330.48729909.566330.14729922.188331.5545 9934.73329.99459951.119318.5558
9960.053315.02059967.337313.02389982.314307.82619986.567306.85779997.292 306.133
10000.03306.460810013.62310.739210026.87313.3461 10066.4316.645810089.09319.9268
10092.44320.687910105.31326.622410137.15334.473110143.56335.283610156.32335.8119
10194.57341.431210220.08348.226910232.83348.388510249.96349.778710300.99349.3234
#Mann= 3 , 0 , 0
9699.041  0.0458       09699.041  0.0458       010300.99  0.0458       0
#XS Ineff= 2 , 0
       0                               0
Bank Sta=9699.041,10300.99
Exp/Cntr=0.3,0.1

Type RM Length L Ch R = 1 , 13052.5,371.433500,371.433500,371.433500
XS GIS Cut Line= 6
468913.890384227748335.696026057468588.722002476748373.586257309
468490.246496707748383.015342548 468453.34338823748388.908239901
468411.435490102748398.223884299 468313.61062932748427.533752754
#Sta/Elev= 30
9599.832330.51879618.875330.68939649.117329.79149669.278329.9438 9699.52330.7194
9729.707330.63489739.769329.44579780.019 329.6389800.143329.0801 9830.33329.3327
9840.393328.50559880.642328.85059890.704328.36599930.947328.0987 9940.99322.3266
9951.033315.88719961.076311.8424 9971.12310.19069981.163305.19079991.206303.8856
10001.25304.7503 10011.3306.116710021.36313.496110031.45317.403410102.79 332.596
10123.47337.708910133.83339.927910154.63345.351410186.13350.868410208.58353.0301
#Mann= 3 , 0 , 0
9599.832    0.06       09599.832    0.06       010208.58    0.06       0
#XS Ineff= 2 , 0
       0                               0
Bank Sta=9599.832,10208.58
Exp/Cntr=0.3,0.1

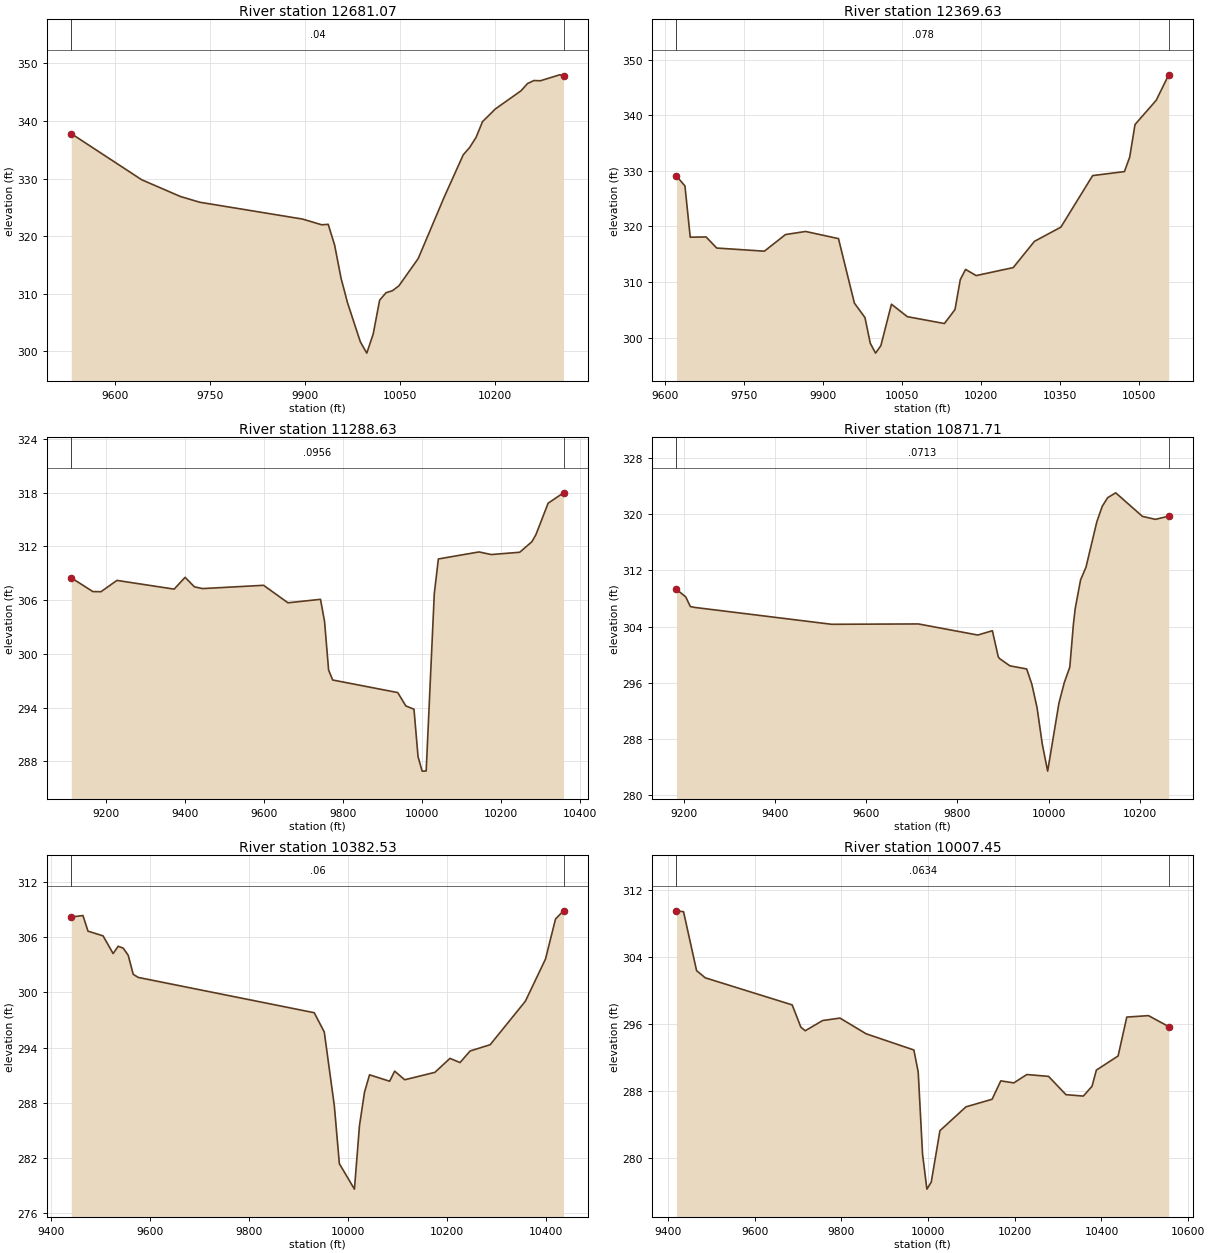
Type RM Length L Ch R = 1 ,12681.07,311.440400,311.440400,311.440400
XS GIS Cut Line= 2
 469034.59097148748112.249829585 468268.96597151747974.228996227
#Sta/Elev= 30
9530.978337.79749642.336329.78369703.303 326.8889733.786325.88859896.365322.9611
9926.849321.9641 9937.01322.04839947.171318.43479957.333312.68319967.494308.4455
9987.816301.63719997.977299.671410008.14303.0009 10018.3308.871510028.46310.1685
10038.62310.517710048.78311.368410079.27316.107410119.91326.6696 10150.4334.1136
10160.56335.396210170.72337.154710180.88339.8836 10201.2342.091410241.85345.2534
10252.01346.503410262.17347.025810272.33346.983710302.81348.016110308.94347.8964
#Mann= 3 , 0 , 0
9530.978    0.04       09530.978    0.04       010308.94    0.04       0
#XS Ineff= 2 , 0
       0                               0
Bank Sta=9530.978,10308.94
Exp/Cntr=0.3,0.1

Type RM Length L Ch R = 1 ,12369.63,1081.002200,1081.002200,1081.002200
XS GIS Cut Line= 2
469071.049304813747713.812329575468141.361804813747794.541496232
#Sta/Elev= 30
9622.378329.05849638.488327.28269648.526318.05769678.639318.09969698.714316.1056
9789.053315.54139829.203318.53589867.297319.08659929.579317.80279959.692306.2059
9979.768 303.6039989.805298.98669999.843297.204910009.88298.544410029.96306.0059
10060.07303.760710130.33302.530310150.41305.035410160.44310.422610170.48312.2626
10190.56311.154110260.82312.587910300.97317.305610351.16319.866510411.39329.1387
10471.61329.857110481.65332.475510491.69338.321710531.84342.674910555.56 347.261
#Mann= 3 , 0 , 0
9622.378   0.078       09622.378   0.078       010555.56   0.078       0
#XS Ineff= 2 , 0
       0                               0
Bank Sta=9622.378,10555.56
Exp/Cntr=0.3,0.1

Type RM Length L Ch R = 1 ,11288.63,416.916400,416.916400,416.916400
XS GIS Cut Line= 2
 469058.02847147 747198.18732959 467847.09097147747487.249829575
#Sta/Elev= 30
9112.307308.49249166.826306.95879187.387306.94069227.786308.20529372.445307.2311
9400.062308.5456 9423.85307.48689444.412307.29089598.626307.65749660.312 305.704
 9742.56306.0931 9752.84303.62959763.121298.19169773.402297.08359937.898295.6803
 9958.46294.18759979.022293.81719989.303288.52799999.584286.912210003.03 286.906
10009.86286.921510030.43306.749210040.71310.598910143.52311.384110174.36311.0912
10246.33311.346710277.17312.518810287.45313.317410318.29 316.82610357.27317.9847
#Mann= 3 , 0 , 0
9112.307  0.0956       09112.307  0.0956       010357.27  0.0956       0
#XS Ineff= 2 , 0
       09805.248                       0
Bank Sta=9112.307,10357.27
Exp/Cntr=0.3,0.1

Type RM Length L Ch R = 1 ,10871.71,489.177600,489.177600,489.177600
XS GIS Cut Line= 6
469055.424304813747179.958162919468563.236804813747166.937329561
 468495.52847147747156.520662919468434.515654325747125.122318462
468326.805925339747040.316098109468059.534683794746876.573736042
#Sta/Elev= 30
9183.381309.31169203.812308.23389213.816306.86669223.819306.73319523.924304.3311
9714.427 304.3819844.717302.79999876.737303.41589889.637299.71399892.208299.4626
9915.288298.40889952.063297.9641 9963.47295.76619974.877292.43349986.284287.2605
 9998.07283.404110022.91293.114510034.77296.063810046.64298.220610054.57304.3352
10058.51306.555610070.37310.670410082.24312.474410105.97318.941110117.84321.1425
10129.71 322.37210147.44323.067910206.04319.715710234.47319.286910263.74319.7435
#Mann= 3 , 0 , 0
9183.381  0.0713       09183.381  0.0713       010263.74  0.0713       0
#XS Ineff= 2 , 0
       09824.179                       0
Bank Sta=9183.381,10263.74
Exp/Cntr=0.3,0.1

Type RM Length L Ch R = 1 ,10382.53,375.078700,375.078700,375.078700
XS GIS Cut Line= 2
469188.236804813746851.833162919468209.070138156746677.353996232
#Sta/Elev= 30
9441.512308.19949465.114308.36329475.272306.66649505.745 306.151 9526.06304.2298
9536.217305.02129546.375304.82339556.532304.0461 9566.69301.97259576.847301.6359
 9932.36297.80079952.675295.7098 9972.99 287.6949983.148281.397710013.62278.6316
10023.78285.521910033.94289.156710044.09291.052510084.72290.356910094.88291.4538
 10115.2290.515810176.14291.320710206.61  292.8410226.93 292.38410247.24293.6387
10287.87294.326210358.98299.050810399.61303.629910419.92307.9906 10436.1308.8731
#Mann= 3 , 0 , 0
9441.512    0.06       09441.512    0.06       0 10436.1    0.06       0
#XS Ineff= 2 , 0
       0                10106.87       0
Bank Sta=9441.512,10436.1
Exp/Cntr=0.3,0.1

Type RM Length L Ch R = 1 ,10007.45,334.954000,334.954000,334.954000
XS GIS Cut Line= 2
469391.361804813746497.666496232468258.549304843746422.145662904
#Sta/Elev= 30
9419.688309.47399436.086309.36559466.152302.32739486.197301.47189686.641 298.238
9706.685295.57489716.707 295.1479756.796296.36939796.885296.66259857.018294.7904
9967.262292.85159977.285290.22479987.307280.39589997.329276.231510007.35277.0682
 10027.4283.214310087.53286.062710147.66286.964410167.71289.164610197.77288.9214
10227.84289.921110277.95289.698210318.04287.513710358.13287.346810378.17288.5188
10388.19290.447810438.31292.138510458.35296.782610508.46296.955210555.01295.6437
#Mann= 3 , 0 , 0
9419.688  0.0634       09419.688  0.0634       010555.01  0.0634       0
#XS Ineff= 2 , 0
       09943.839        10246.14       0
Bank Sta=9419.688,10555.01
Exp/Cntr=0.3,0.1

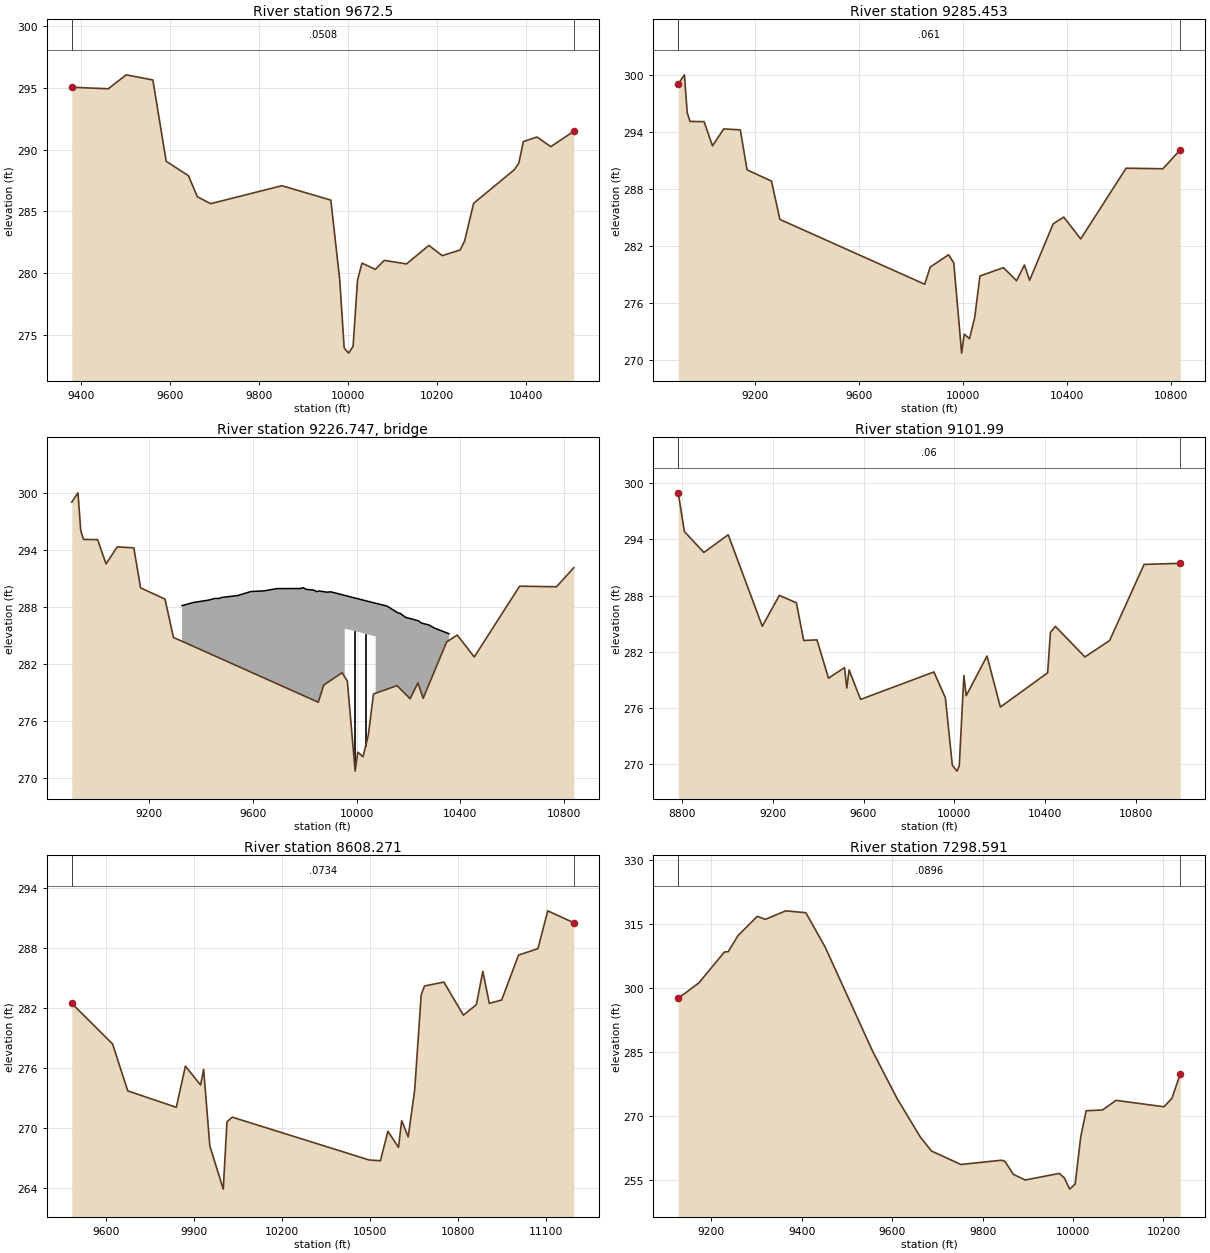
Type RM Length L Ch R = 1 ,  9672.5,387.047000,387.047000,387.047000
XS GIS Cut Line= 6
469327.091485409746121.871429296469154.815301293746130.691332911
468708.257523192746144.621345317468506.996649874746158.305243813
468348.051958768746180.911239681468204.911736811746215.779814135
#Sta/Elev= 30
9379.357295.0501 9461.59294.9283 9501.63296.05829561.685295.6429  9591.7289.0522
9641.724 287.8819661.734286.18169691.748285.61619851.826287.0733 9961.88285.9061
9981.889279.45279991.894273.9226 10001.9273.506910011.92274.057210021.94279.4336
10031.97280.799710062.04280.290910082.08  281.02 10132.2280.736710182.32282.2362
10212.44 281.40610252.72281.865710262.78282.600810282.95285.646910374.32288.3634
10384.55 288.89910394.79290.651110425.49 291.01910456.49290.240110508.32291.4874
#Mann= 3 , 0 , 0
9379.357  0.0508       09379.357  0.0508       010508.32  0.0508       0
#XS Ineff= 2 , 0
       09913.713        10131.74       0
Bank Sta=9379.357,10508.32
Exp/Cntr=0.3,0.1

Type RM Length L Ch R = 1 ,9285.453,183.462400,183.462400,183.462400
XS GIS Cut Line= 5
469566.672858059746057.019794852469408.252719164745675.075350404
468594.813849092 745781.97065109468346.913051426745812.825346127
468164.763135821 746226.29062818
#Sta/Elev= 30
8902.229299.07968926.068300.06498936.894296.0599 8947.72295.1445 9001.85295.1207
9034.328292.55969077.633 294.3549141.506294.25399167.607290.02869261.676288.8407
9294.154 284.7949852.403277.95039873.734 279.7689944.336281.06239964.508280.1965
9994.765270.674210004.85272.678510025.02272.1977 10045.2274.436910065.37278.8201
10156.12279.704110206.51278.317210236.74 279.987 10256.9278.365810347.59284.3244
10388.35 285.04210453.91282.735810628.75 290.20510770.81290.145410837.78292.1604
#Mann= 3 , 0 , 0
8902.229   0.061       08902.229   0.061       010837.78   0.061       0
#XS Ineff= 2 , 0
       09920.477        10114.03       0
Bank Sta=8902.229,10837.78
Exp/Cntr=0.3,0.1

Type RM Length L Ch R = 3 ,9226.747,,,
BEGIN DESCRIPTION:
END DESCRIPTION:
Bridge Culvert--1,0,-1,-1, 0
Deck Dist Width WeirC Skew NumUp NumDn MinLoCord MaxHiCord MaxSubmerge Is_Ogee
23.656200,136.150000,2.6,0, 31, 31, , , 0.95, 0, 0,0,,
 9327.44 9370.18 9430.82 9451.04 9471.25 9481.36 9542.00 9592.53 9643.07 9693.60
 9784.56 9794.67 9804.78 9835.10 9845.20 9855.31 9885.63 9901.17 9954.75 9954.75
10073.8410073.8410118.0910158.5110168.6210188.8110239.0410249.0910279.2310298.87
10356.48
  288.15  288.48  288.74  288.90  288.92  289.02  289.22  289.64  289.71  289.95
  289.96  290.05  289.87  289.80  289.63  289.70  289.57  289.61  289.23  289.23
  288.40  288.40  288.10  287.40  287.33  286.92  286.55  286.32  286.11  285.80
  285.18
 -711.85 -711.52 -711.26 -711.10 -711.08 -710.98 -710.78 -710.36 -710.29 -710.05
 -710.04 -709.95 -710.13 -710.20 -710.37 -710.30 -710.43 -710.39 -710.77  285.73
  284.90 -711.60 -711.90 -712.60 -712.67 -713.08 -713.45 -713.68 -713.89 -714.20
 -714.82
 9327.44 9370.18 9430.82 9451.04 9471.25 9481.36 9542.00 9592.53 9643.07 9693.60
 9784.56 9794.67 9804.78 9835.10 9845.20 9855.31 9885.63 9901.17 9943.92 9943.92
10063.0110063.0110118.0910158.5110168.6210188.8110239.0410249.0910279.2310298.87
10356.48
  288.15  288.48  288.74  288.90  288.92  289.02  289.22  289.64  289.71  289.95
  289.96  290.05  289.87  289.80  289.63  289.70  289.57  289.61  289.31  289.31
  288.48  288.48  288.10  287.40  287.33  286.92  286.55  286.32  286.11  285.80
  285.18
 -711.85 -711.52 -711.26 -711.10 -711.08 -710.98 -710.78 -710.36 -710.29 -710.05
 -710.04 -709.95 -710.13 -710.20 -710.37 -710.30 -710.43 -710.39 -710.69  285.81
  284.98 -711.52 -711.90 -712.60 -712.67 -713.08 -713.45 -713.68 -713.89 -714.20
 -714.82
Pier Skew, UpSta & Num, DnSta & Num=  ,9993.78, 2 ,9982.95, 2 , 0 , 0 , 0 ,,
    4.00    4.00
 -711.04  288.96
    4.00    4.00
 -710.96  289.04
Pier Skew, UpSta & Num, DnSta & Num=  ,10034.81, 2 ,10023.98, 2 , 0 , 0 , 0 ,,
    4.00    4.00
 -711.33  288.67
    4.00    4.00
 -711.25  288.75
BR Coef=-1 , 0 , 0 ,, 0 ,,,0.8,0,1,0,
WSPro=,,,, 1 ,,,, 0 ,,,, 0 ,,,,-1 ,-1 ,-1 , 0 , 0 , 0 , 0 , 0
BC Design=,, 0 ,, 0 ,,,,,,

Type RM Length L Ch R = 1 , 9101.99,493.719100,493.719100,493.719100
XS GIS Cut Line= 5
469595.621064067746040.288024023469389.313579381745502.583872586
468795.657129347745579.840533882468352.912730724745663.725524008
468127.218286306746201.919968471
#Sta/Elev= 30
8784.902298.96498811.988294.83628897.674292.60449004.782294.49049154.733284.7339
9229.709288.02379304.684287.23699336.817283.21779395.429283.27919445.851279.1952
9516.441280.31869526.525278.1452 9536.61280.07799587.031276.9294 9909.73279.8559
9960.157 277.1059990.691269.907810011.05269.279110021.22269.820710041.58279.4803
10051.76277.327510143.36281.558510202.08276.114110410.11279.767210422.34284.0749
10444.02284.716310574.15281.459910682.58283.2064 10834.4291.329310993.71291.4438
#Mann= 3 , 0 , 0
8784.902    0.06       08784.902    0.06       010993.71    0.06       0
#XS Ineff= 2 , 0
       09917.072        10128.08       0
Bank Sta=8784.902,10993.71
Exp/Cntr=0.3,0.1

Type RM Length L Ch R = 1 ,8608.271,1309.680300,1309.680300,1309.680300
XS GIS Cut Line= 6
469240.233332574745004.900292531468790.870531797745120.862839729
468744.328711987745146.105976224468713.537307411745171.989278734
468372.443980724745589.940801799468109.857175201746145.496357352
#Sta/Elev= 30
9483.777 282.4589622.922278.40389674.614273.72659840.086272.08719871.155276.1937
9922.938274.31139933.294275.8749 9954.42268.2269 10000.2263.9237 10012.8270.6362
10030.69271.105710497.32266.8327 10535.8 266.75410561.54269.694810597.43268.0877
10608.49270.748510630.61269.126710652.74273.822910674.86 283.30210685.92284.1895
10752.28284.580610818.65281.283610862.89282.321410885.01285.657610907.13282.4605
10949.22282.789911006.68287.273311073.05287.922411106.23291.690811195.26290.4996
#Mann= 3 , 0 , 0
9483.777  0.0734       09483.777  0.0734       011195.26  0.0734       0
#XS Ineff= 2 , 0
       09890.881        10392.64       0
Bank Sta=9483.777,11195.26
Exp/Cntr=0.3,0.1

Type RM Length L Ch R = 1 ,7298.591,410.826700,410.826700,410.826700
XS GIS Cut Line= 6
468326.523841858744674.547283262468125.677749813745055.988021195
 467998.08449626745358.264935881467978.515065163745408.429827332
467956.091431946 745450.50762932467814.527314067745656.781079575
#Sta/Elev= 30
9126.446297.52139172.164301.14179228.672308.38549237.034308.44339258.498312.1977
9301.425316.73389319.084316.0229 9364.29318.02219408.743317.5798 9451.67309.5008
9556.417285.15199610.705 274.0379662.135265.02339686.713261.75529751.839258.5989
9842.138259.59249849.529259.30049867.853256.28919894.123 254.956 9969.59256.5016
9980.922255.43659992.622252.819710004.78254.022410016.93265.034610029.08271.1827
10065.48 271.36710094.95273.617210201.12272.115310218.81274.097210237.34279.8304
#Mann= 3 , 0 , 0
9126.446  0.0896       09126.446  0.0896       010237.34  0.0896       0
#XS Ineff= 2 , 0
       0                               0
Bank Sta=9126.446,10237.34
Exp/Cntr=0.3,0.1

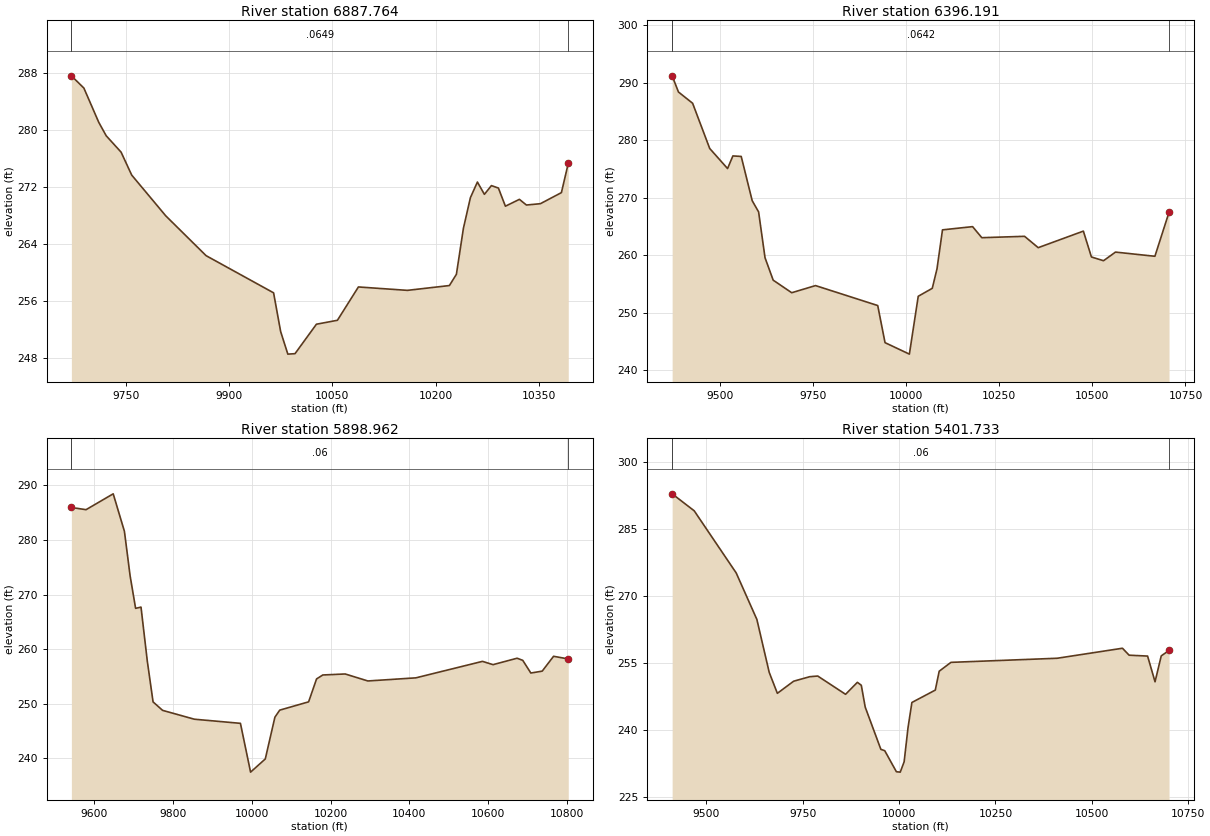
Type RM Length L Ch R = 1 ,6887.764,491.573500,491.573500,491.573500
XS GIS Cut Line= 6
467938.149999291 744858.19890365467864.128297359745039.187083378
467841.457125545745143.945598528467834.373101443745167.984674945
467829.997202843745181.008127481467762.368749261745554.813486978
#Sta/Elev= 30
9671.215287.64219689.367285.92079710.975281.11029721.779279.22159743.387276.9235
9758.786273.70389808.211267.98139866.755262.38749964.786257.16529975.038 251.725
9985.463248.55679995.888248.619710026.96 252.75710057.45253.309210087.93  257.99
10159.07257.512510220.04258.1884 10230.2259.768210240.37266.222510250.53270.5309
10260.69272.724810270.85270.998710281.02272.223810291.18271.881510301.34269.3307
10321.67270.294110331.83269.496610352.15269.684310382.64271.236410392.61275.3502
#Mann= 3 , 0 , 0
9671.215  0.0649       09671.215  0.0649       010392.61  0.0649       0
#XS Ineff= 2 , 0
       09866.557                       0
Bank Sta=9671.215,10392.61
Exp/Cntr=0.3,0.1

Type RM Length L Ch R = 1 ,6396.191,497.228700,497.228700,497.228700
XS GIS Cut Line= 6
467849.148432106744694.611115962467518.363433778744930.544739962
467321.542761952745168.940823033467216.048441023745258.054346174
467027.928875566745359.048157915466779.103720605745452.242301509
#Sta/Elev= 30
9370.812291.23579387.784288.42089425.835286.45969471.753278.59059519.735275.0924
 9534.04277.29389556.408277.1998 9585.86269.50849603.134 267.5439620.407259.5643
9642.257255.66679692.074253.47589756.069254.71999923.162251.24649942.832244.7854
10008.22242.787510032.03252.858310069.73254.242910082.44257.636110097.19264.4215
 10178.1 264.98110202.83263.056710317.72263.296610354.36261.320910475.69264.2009
10497.35259.699810529.86259.048410561.97260.549810667.91259.820910705.83267.4818
#Mann= 3 , 0 , 0
9370.812  0.0642       09370.812  0.0642       010705.83  0.0642       0
#XS Ineff= 2 , 0
       09785.321        10211.39       0
Bank Sta=9370.812,10705.83
Exp/Cntr=0.3,0.1

Type RM Length L Ch R = 1 ,5898.962,497.228800,497.228800,497.228800
XS GIS Cut Line= 6
467451.534722835744390.354718104467199.419872433744627.793909132
466997.694666684744780.116204411466932.804836601 744835.58857353
466656.040005535745148.045585006466541.308762223745259.930691779
#Sta/Elev= 30
9541.499285.9685 9578.77285.56799647.796288.47089676.276281.59979690.685273.4808
  9704.7267.49569718.428 267.7269734.472257.80539749.068250.36519773.342248.8127
9854.092247.19259971.055246.43959996.863237.503410034.23239.913910058.66247.5644
10070.87248.853610144.33250.375910164.52254.570710180.41255.295910237.33255.4775
10294.92 254.19810416.87254.769210586.16257.787710612.95257.185810674.14258.3637
10688.55257.970310709.03255.652510737.91255.999310766.79258.717110804.14258.2336
#Mann= 3 , 0 , 0
9541.499    0.06       09541.499    0.06       010804.14    0.06       0
#XS Ineff= 2 , 0
       09880.502        10207.82       0
Bank Sta=9541.499,10804.14
Exp/Cntr=0.3,0.1

Type RM Length L Ch R = 1 ,5401.733,0.000000,0.000000,0.000000
XS GIS Cut Line= 6
466832.710071713743993.435997874466738.365399033744212.811831772
466691.882523924744360.762150258466602.057488531744816.858845428
 466493.08398813745048.323193267 466392.47984764745188.571020812
#Sta/Elev= 30
9411.413292.87719468.635289.08359577.546 275.1929631.214264.79229663.202252.9642
9684.321248.27819726.559250.98689768.215251.99299789.039252.14339861.271248.0565
9891.848250.73519902.035250.08159912.222  245.199952.749235.76199962.849235.4505
9993.056230.7476 10003.1230.660910013.16  232.9710023.23240.597410033.29246.2309
10093.96248.998710104.09253.2181 10134.6255.198610409.98256.115910579.43258.3552
10596.74256.801510644.62256.605810663.95250.857410680.05256.653810700.21 257.863
#Mann= 3 , 0 , 0
9411.413    0.06       09411.413    0.06       010700.21    0.06       0
#XS Ineff= 2 , 0
       0                10164.12       0
Bank Sta=9411.413,10700.21
Exp/Cntr=0.3,0.1